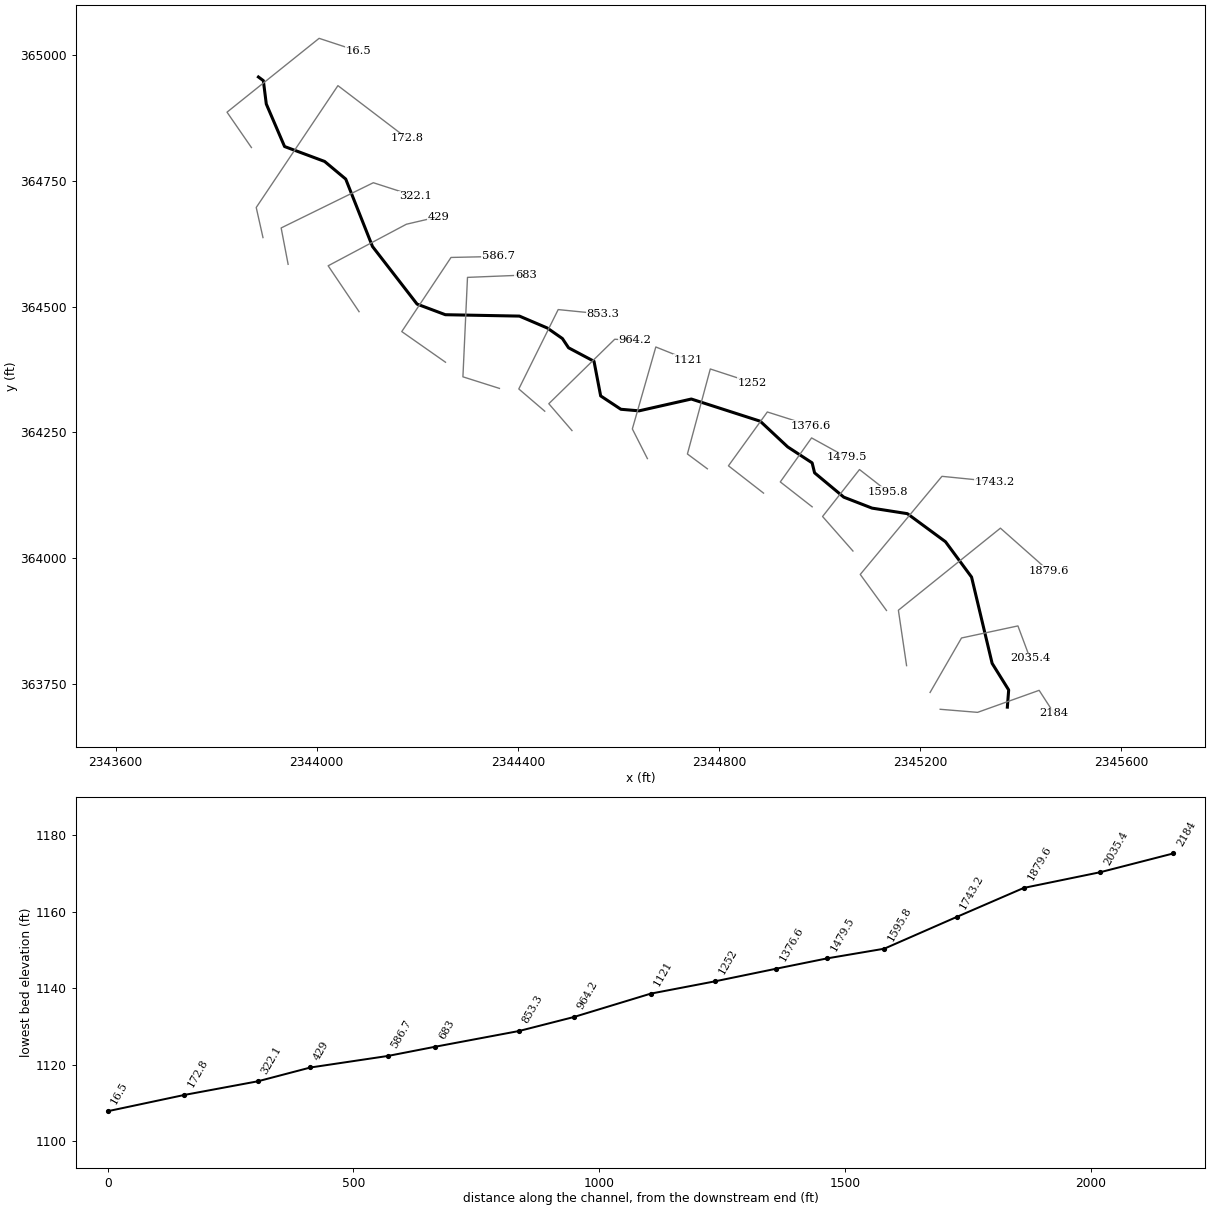
--- ROARINGRUN.prj (project) ---

Proj Title=ROARINGRUN
Current Plan=p01
Default Exp/Contr=0,0
English Units
Geom File=g01
Flow File=f01
Plan File=p01
BEGIN DESCRIPTION:
END DESCRIPTION:
DSS Export Rating Curves= 0
DSS Export Rating Curve Sorted= 0
DSS Export Volume Flow Curves= 0
DXF OffsetX= 0
DXF OffsetY= 0
DXF ScaleX= 0
DXF ScaleY= 0

--- ROARINGRUN.p01 (plan) ---

Plan Title=Floodplain
Program Version=4.00
Geom File=g01
Flow File=f01
K Sum by GR=0
Std Step Tol=0.01
Critical Tol=0.01
Num of Std Step Trials=20
Max Error Tol=0.3
Flow Tol Ratio=0.001
Split Flow NTrial=30
Split Flow Tol=0.02
Split Flow Ratio=0.02
Log Output Level=0
Friction Slope Method=1
Unsteady Friction Slope Method=2
Unsteady Bridges Friction Slope Method=1
Global Log Level=0
CheckData=False
Run HTab=0
Run UNet=0
Run PostProcess=0
UNET Theta=0
UNET Theta Warmup=0
UNET ZTol=0
UNET ZSATol=0
UNET MxIter=0
UNET MaxInSteps=0
UNET DtIC=0
UNET DtMin=0
UNET MaxCRTS=0
UNET WFStab=0
UNET SFStab=0
UNET WFX=0
UNET SFX=0
UNET DSS MLevel=0
UNET DZMax Abort=0
UNET Convert EG Bridges=0
UNET Use Existing IB Tables=0
UNET Froude Limit=0
UNET Froude Power=0
Write IC File=0
Echo Input=False
Echo Output=False
Write Detailed=0

--- ROARINGRUN.f01 (steady flow) ---

Flow Title=NFF Regression Equation
Program Version=4.00
Number of Profiles=1
Profile Names=P100yr
River Rch & RM=ROARINGRUN,Main      ,2184
511.2459
River Rch & RM=ROARINGRUN,Main      ,2035.4
511.2459
River Rch & RM=ROARINGRUN,Main      ,1743.2
625.9356
River Rch & RM=ROARINGRUN,Main      ,586.7
640.8412
River Rch & RM=ROARINGRUN,Main      ,172.8
641.4229
Boundary for River Rch & Prof#=ROARINGRUN,Main      ,1
Up Type=0
Dn Type=3
Dn Slope=0.02757

--- ROARINGRUN.g01 (geometry) ---

Geom Title=USGS 10m DEM
Program Version=4.10

River Reach=ROARINGRUN      ,Main
Reach XY= 30
     2345373.736      363703.735     2345376.366       363737.93
      2345343.45      363790.818     2345302.555      363962.416
     2345250.715      364032.722     2345174.803      364088.581
     2345104.639      364099.568      2345048.47      364121.348
      2344990.31      364169.785     2344985.449      364189.577
     2344936.838      364221.348     2344882.225      364272.436
     2344745.174      364316.569     2344641.242      364293.072
     2344605.044      364296.197     2344564.835      364322.775
     2344551.626      364391.576     2344500.951      364418.514
     2344488.805      364436.816     2344458.658      364457.852
      2344403.25      364481.513     2344255.923      364484.284
     2344199.673      364505.378     2344111.001      364619.962
     2344057.764      364754.082     2344015.819      364789.102
     2343936.132       364818.79     2343899.778      364903.388
     2343893.934      364949.842     2343884.162        364957.1

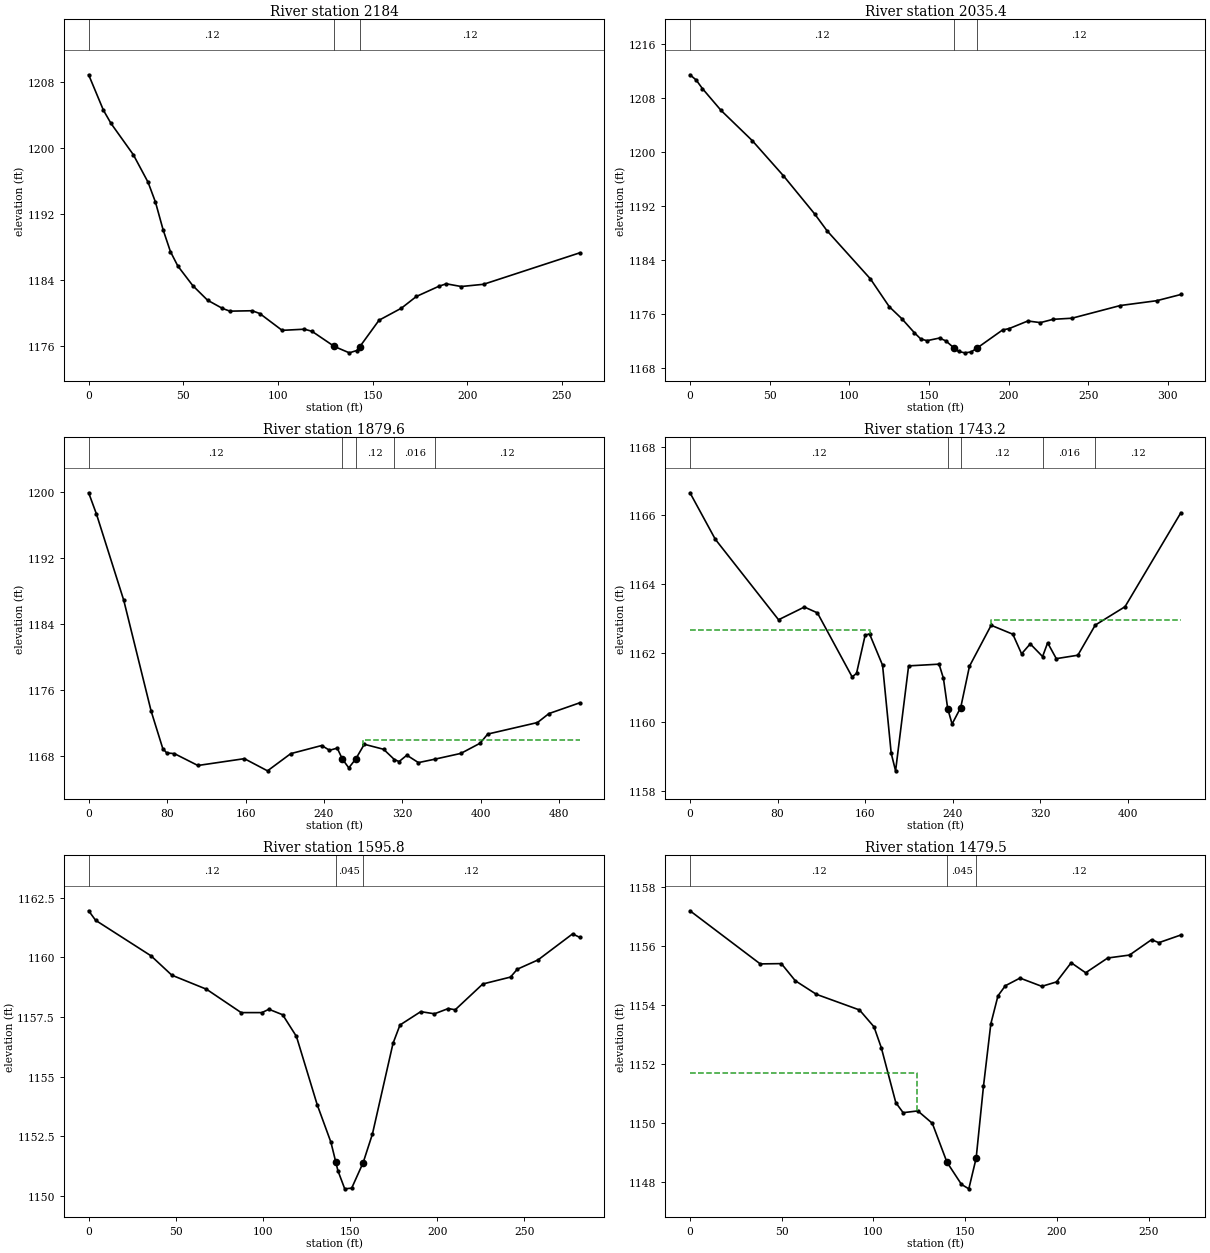
Type RM Length L Ch R = 1 ,2184    ,151.6,148.6,144.5
XS GIS Cut Line= 4
     2345240.143      363699.486     2345314.504      363693.366
     2345436.945      363737.177     2345466.632      363691.343
#Sta/Elev= 30
       0 1208.92     7.8 1204.62    11.8 1203.02    23.6 1199.22    31.4 1195.87
    35.3 1193.46    39.3 1190.13    43.2 1187.46    47.1 1185.71      55 1183.33
    62.8 1181.56    70.7 1180.56    74.6 1180.23    86.4 1180.28    90.4 1179.94
   102.2  1177.9     114 1178.04     118 1177.78   129.8 1175.94   137.7 1175.17
   141.6 1175.45  143.241175.918   153.4 1179.13   165.2 1180.59   173.1 1182.01
     185 1183.25   188.9 1183.55   196.8 1183.22   208.6 1183.49   259.3  1187.3
#Mann= 3 ,-1 , 0
       0     .12       0   129.8    .045       0  143.24     .12       0
Bank Sta=129.8,143.24
XS Rating Curve= 0 ,0
Exp/Cntr=0.3,0.1

Type RM Length L Ch R = 1 ,2035.4  ,145.3,155.8,166.2
XS GIS Cut Line= 4
     2345220.039      363732.958     2345282.539      363841.291
     2345394.757      363865.302     2345418.716      363801.239
#Sta/Elev= 30
       0  1211.4     3.9 1210.62     7.8 1209.36    19.5 1206.13    39.1 1201.66
    58.6 1196.48    78.2 1190.84      86 1188.34   113.3  1181.2   125.1  1177.1
     133 1175.32   140.9 1173.24   144.9 1172.32   148.8 1172.07   156.7 1172.46
   160.7 1172.03  165.641171.014   168.6 1170.47   172.6 1170.27   176.5  1170.4
   180.5 1171.02   196.3 1173.66   200.3 1173.85   212.1 1174.98     220 1174.74
     228 1175.23   239.8 1175.39   270.2 1177.27     293 1177.98   308.2  1178.9
#Mann= 3 ,-1 , 0
       0     .12       0  165.64    .045       0   180.5     .12       0
Bank Sta=165.64,180.5
XS Rating Curve= 0 ,0
Exp/Cntr=0.3,0.1

Type RM Length L Ch R = 1 ,1879.6  ,131.8,136.4,140.8
XS GIS Cut Line= 4
     2345173.303      363786.291     2345157.006      363896.502
     2345359.935      364059.729     2345456.324      363974.407
#Sta/Elev= 30
       0 1199.96       8 1197.36    35.8 1186.89    63.7 1173.43    75.6 1168.87
    79.6 1168.34    87.5 1168.25   111.4 1166.81   158.8 1167.64   182.4 1166.16
   206.1 1168.25   237.7 1169.24   245.6 1168.66   253.5 1168.92  258.771167.585
   265.3 1166.52  272.441167.615   281.1 1169.39   300.8 1168.78   311.8 1167.53
   316.6 1167.29   324.5 1168.06   336.3 1167.16  353.011167.576   379.6 1168.28
   399.1 1169.51     407 1170.63   457.7 1172.03   469.4 1173.12   500.6 1174.42
#Mann= 5 ,-1 , 0
       0     .12       0  258.77    .045       0  272.44     .12       0
   311.8    .016       0  353.01     .12       0
#XS Ineff= 2 , 0
                          279.88         1169.85
Permanent Ineff=
       F       F
Bank Sta=258.77,272.44
XS Rating Curve= 0 ,0
Exp/Cntr=0.3,0.1

Type RM Length L Ch R = 1 ,1743.2  ,146.4,147.4,147.7
XS GIS Cut Line= 4
     2345133.299      363896.031      2345081.15       363967.68
      2345243.65      364162.819     2345348.924      364152.281
#Sta/Elev= 30
       0 1166.66    23.1 1165.31    80.9 1162.97   104.5 1163.34   116.4 1163.17
   148.1 1161.31   152.1 1161.41     160 1162.52     164 1162.56   175.9 1161.65
   183.8 1159.09   187.8 1158.58   199.7 1161.63   227.5 1161.68   231.5 1161.27
   235.4 1160.39   239.4 1159.94   247.3 1160.42   255.3 1161.62   275.1 1162.81
   294.9 1162.55   302.9 1161.98   310.8 1162.27  322.071161.901   326.7  1162.3
   334.6 1161.84   354.3 1161.94  370.181162.815   397.4 1163.35   448.4 1166.08
#Mann= 5 ,-1 , 0
       0     .12       0   235.4    .045       0   247.3     .12       0
  322.07    .016       0  370.18     .12       0
#XS Ineff= 2 , 0
          164.09 1162.68  275.03         1162.95
Permanent Ineff=
       F       F
Bank Sta=235.4,247.3
XS Rating Curve= 0 ,0
Exp/Cntr=0.3,0.1

Type RM Length L Ch R = 1 ,1595.8  ,115.2,116.4,117.4
XS GIS Cut Line= 4
     2345066.632       364014.26     2345006.197       364082.93
     2345079.618      364176.317     2345135.903      364132.489
#Sta/Elev= 30
       0 1161.95       4 1161.55    35.8 1160.06    47.7 1159.25    67.6 1158.66
    87.5 1157.68    99.4 1157.68   103.4 1157.82   111.3 1157.59   119.2 1156.68
   131.1 1153.82     139 1152.24  141.751151.419     143 1151.05   146.9 1150.29
   150.9 1150.32  157.481151.391   162.8 1152.59   174.6 1156.39   178.6 1157.16
   190.5 1157.72   198.4 1157.63   206.3 1157.85   210.3  1157.8   226.1 1158.88
     242 1159.17   245.9  1159.5   257.8 1159.89   277.6 1160.98   281.6 1160.84
#Mann= 3 ,-1 , 0
       0     .12       0  141.75    .045       0  157.48     .12       0
Bank Sta=141.75,157.48
XS Rating Curve= 0 ,0
Exp/Cntr=0.3,0.1

Type RM Length L Ch R = 1 ,1479.5  ,103,102.9,102.6
XS GIS Cut Line= 4
     2344985.491      364102.185     2344922.123      364151.708
     2344984.341       364239.26     2345054.132      364200.718
#Sta/Elev= 30
       0 1157.18    38.3 1155.38    49.8 1155.39    57.4 1154.81    68.9 1154.35
    92.4 1153.82   100.3 1153.25   104.3 1152.54   112.2 1150.68   116.2 1150.34
   124.2  1150.4   132.1 1149.98   140.1 1148.66     148 1147.91     152 1147.76
     156  1148.8     160 1151.24     164 1153.35   167.9  1154.3   171.9 1154.64
   179.9  1154.9   191.8 1154.62   199.8 1154.77   207.8 1155.42   215.7 1155.08
   227.7 1155.58   239.6 1155.68   251.6  1156.2   255.6  1156.1   267.6 1156.36
#Mann= 3 ,-1 , 0
       0     .12       0   140.1    .045       0     156     .12       0
#XS Ineff= 2 , 0
          123.53  1151.7
Permanent Ineff=
       F       F
Bank Sta=140.1,156
XS Rating Curve= 0 ,0
Exp/Cntr=0.3,0.1

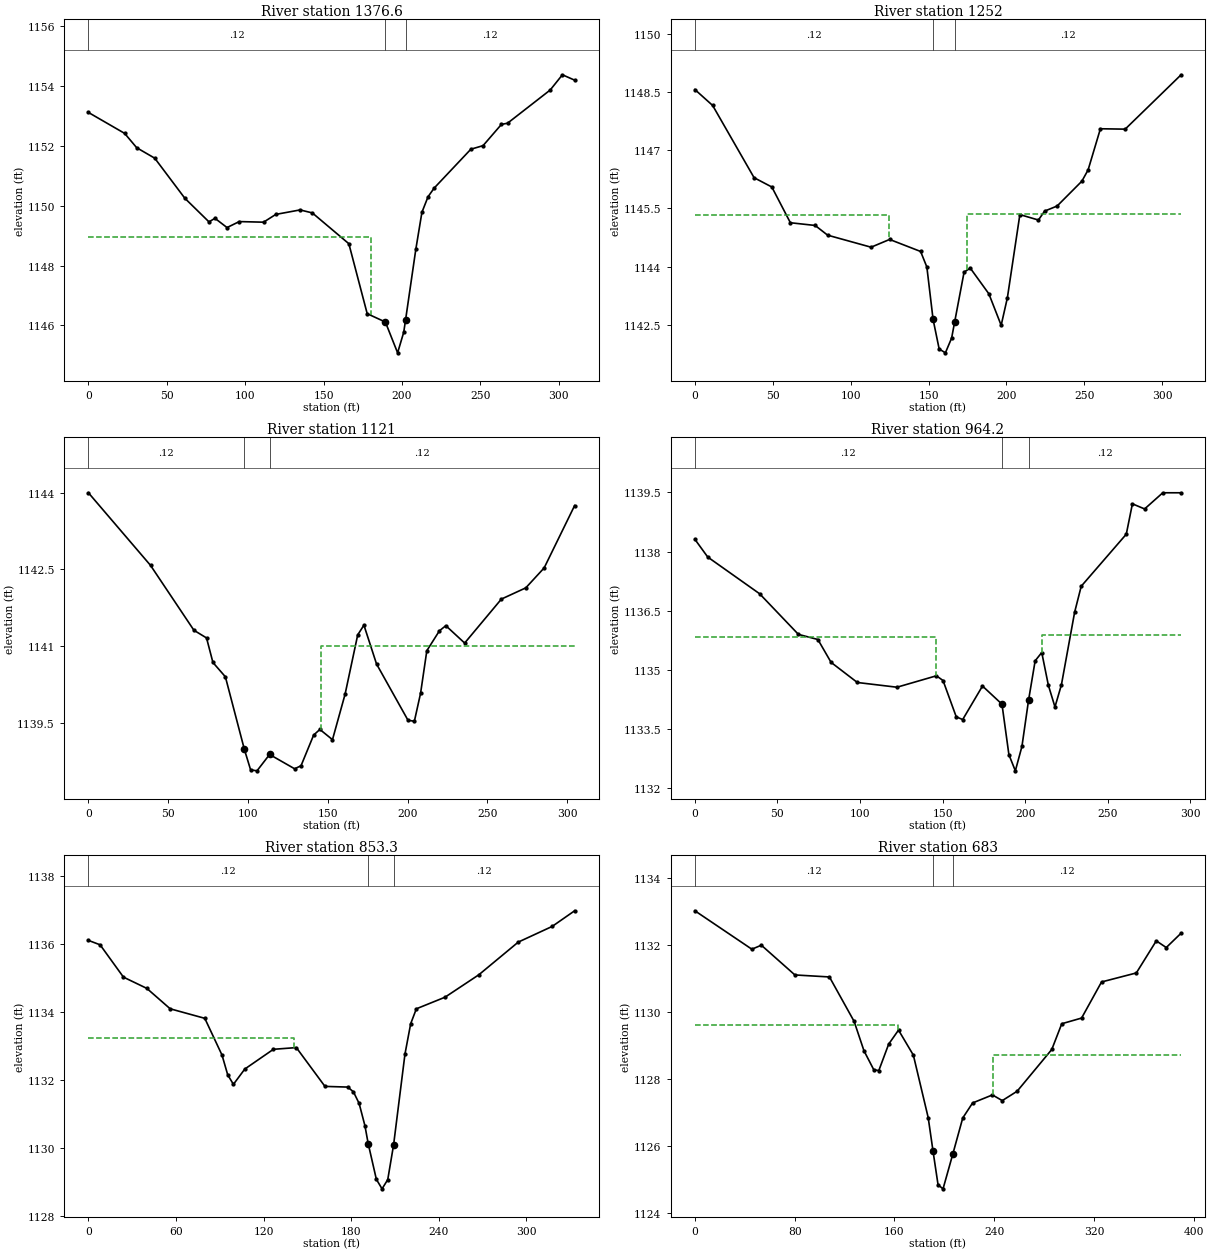
Type RM Length L Ch R = 1 ,1376.6  ,115.8,124.6,132.4
XS GIS Cut Line= 4
     2344888.789      364129.442     2344818.999      364183.739
      2344896.32      364290.822     2344981.736      364263.739
#Sta/Elev= 30
       0 1153.12    23.1 1152.42    30.8 1151.94    42.3 1151.59    61.5 1150.25
    76.9 1149.46    80.7 1149.58    88.4 1149.27    96.2 1149.47   111.7 1149.45
   119.5 1149.71     135 1149.86   142.8 1149.76   166.1 1148.73   177.8 1146.39
   189.4 1146.11   197.2 1145.08   201.1 1145.77  202.291146.188   208.8 1148.54
   212.7 1149.78   216.6  1150.3   220.5 1150.59   243.9 1151.89   251.7 1152.01
   263.4 1152.72   267.3 1152.76   294.5 1153.87   302.3 1154.38   310.1  1154.2
#Mann= 3 ,-1 , 0
       0     .12       0   189.4    .045       0  202.29     .12       0
#XS Ineff= 2 , 0
          180.24 1148.97
Permanent Ineff=
       F       F
Bank Sta=189.4,202.29
XS Rating Curve= 0 ,0
Exp/Cntr=0.3,0.1

Type RM Length L Ch R = 1 ,1252    ,131.3,131,130
XS GIS Cut Line= 4
     2344777.049      364177.802       2344737.4      364207.263
     2344782.887      364376.361     2344866.111      364349.156
#Sta/Elev= 30
       0 1148.56    11.4 1148.15      38 1146.29    49.4 1146.05    61.3 1145.13
    77.2 1145.06    85.2 1144.81   113.1  1144.5     125  1144.7   144.9 1144.39
   148.9 1143.99   152.9 1142.64   156.8 1141.88   160.8 1141.78   164.8 1142.16
  166.791142.584   172.8 1143.86   176.8 1143.96   188.7  1143.3   196.6 1142.49
   200.6  1143.2   208.6 1145.34   220.5  1145.2   224.5 1145.43   232.5 1145.56
   248.4  1146.2   252.4 1146.49   260.3 1147.55   276.2 1147.54   312.1 1148.94
#Mann= 3 ,-1 , 0
       0     .12       0   152.9    .045       0  166.79     .12       0
#XS Ineff= 2 , 0
          124.61 1145.34  174.82         1145.36
Permanent Ineff=
       F       F
Bank Sta=152.9,166.79
XS Rating Curve= 0 ,0
Exp/Cntr=0.3,0.1

Type RM Length L Ch R = 1 ,1121    ,168.1,156.8,145.3
XS GIS Cut Line= 4
     2344657.778      364198.114     2344627.852       364257.09
     2344674.553      364420.111     2344738.507      364394.468
#Sta/Elev= 30
       0    1144    38.9 1142.58    66.1 1141.31      74 1141.16      78 1140.68
    85.8  1140.4    97.7 1138.98   101.6 1138.58   105.6 1138.56   113.5 1138.88
   129.2  1138.6   133.2 1138.66   141.1 1139.26     145 1139.37   152.9 1139.17
   160.8 1140.06   168.7 1141.22   172.6 1141.41   180.5 1140.65   200.2 1139.55
   204.2 1139.53   208.1 1140.08     212 1140.91   219.9  1141.3   223.9  1141.4
   235.7 1141.06   258.7 1141.92     274 1142.14   285.5 1142.53   304.6 1143.75
#Mann= 3 ,-1 , 0
       0     .12       0    97.7    .045       0   113.5     .12       0
#XS Ineff= 2 , 0
                          145.56            1141
Permanent Ineff=
       F       F
Bank Sta=97.7,113.5
XS Rating Curve= 0 ,0
Exp/Cntr=0.3,0.1

Type RM Length L Ch R = 1 ,964.2   ,103.3,110.9,118.1
XS GIS Cut Line= 4
     2344507.778      364253.843     2344461.706      364307.263
     2344592.847      364435.484     2344633.299       364433.01
#Sta/Elev= 30
       0 1138.31     7.8 1137.86    39.2 1136.93    62.7  1135.9    74.5 1135.77
    82.5 1135.19    98.4 1134.68   122.4 1134.56   146.3 1134.85   150.3 1134.73
   158.3 1133.81   162.2 1133.74   174.2 1134.59     186 1134.13   190.2 1132.85
   194.1 1132.44   198.1 1133.06   202.1 1134.23   206.1 1135.23   210.1 1135.44
   214.1 1134.61   218.1 1134.06     222 1134.62     230 1136.46     234 1137.12
   261.3 1138.44     265 1139.21   272.4 1139.08   283.4 1139.49   294.5 1139.49
#Mann= 3 ,-1 , 0
       0     .12       0     186    .045       0   202.1     .12       0
#XS Ineff= 2 , 0
          145.82 1135.84  210.22         1135.88
Permanent Ineff=
       F       F
Bank Sta=186,202.1
XS Rating Curve= 0 ,0
Exp/Cntr=0.3,0.1

Type RM Length L Ch R = 1 ,853.3   ,160.8,170.2,179.6
XS GIS Cut Line= 4
     2344453.611      364292.385     2344402.011      364336.607
      2344480.35      364494.485     2344568.716      364485.614
#Sta/Elev= 30
       0 1136.11       8 1135.98      24 1135.03      40  1134.7      56  1134.1
    79.7 1133.82    91.5 1132.74    95.4 1132.16    99.3 1131.88   107.1 1132.33
   126.7 1132.91   142.4 1132.96     162 1131.82   177.6  1131.8   181.5 1131.66
   185.4 1131.32   189.4 1130.66   191.61130.141   197.2 1129.09   201.1 1128.81
     205 1129.08     209  1130.1   216.8 1132.77   220.7 1133.66   224.6  1134.1
   244.2 1134.44   267.4  1135.1   294.4 1136.06   317.6 1136.52     333 1136.98
#Mann= 3 ,-1 , 0
       0     .12       0   191.6    .045       0     209     .12       0
#XS Ineff= 2 , 0
          140.87 1133.24
Permanent Ineff=
       F       F
Bank Sta=191.6,209
XS Rating Curve= 0 ,0
Exp/Cntr=0.3,0.1

Type RM Length L Ch R = 1 ,683     ,108.3,96.3,83.9
XS GIS Cut Line= 4
     2344363.507      364337.697     2344290.873      364360.736
     2344299.966      364558.531     2344415.591      364563.218
#Sta/Elev= 30
       0 1133.03    45.7 1131.88    53.3    1132    80.2 1131.11   107.9 1131.05
   127.7 1129.72   135.6 1128.84   143.5 1128.27   147.5 1128.25   155.4 1129.04
   163.3 1129.46   175.2 1128.71   187.1 1126.84     191 1125.83     195 1124.83
     199 1124.71   206.9 1125.76   214.8 1126.83   222.7 1127.28   238.6 1127.52
   246.5 1127.35   258.4 1127.63   286.2 1128.88   294.2 1129.65   310.1 1129.82
   326.1  1130.9     354 1131.17     370 1132.13     378 1131.93   389.9 1132.36
#Mann= 3 ,-1 , 0
       0     .12       0     191    .045       0   206.9     .12       0
#XS Ineff= 2 , 0
          163.05 1129.61  239.01         1128.71
Permanent Ineff=
       F       F
Bank Sta=191,206.9
XS Rating Curve= 0 ,0
Exp/Cntr=0.3,0.1

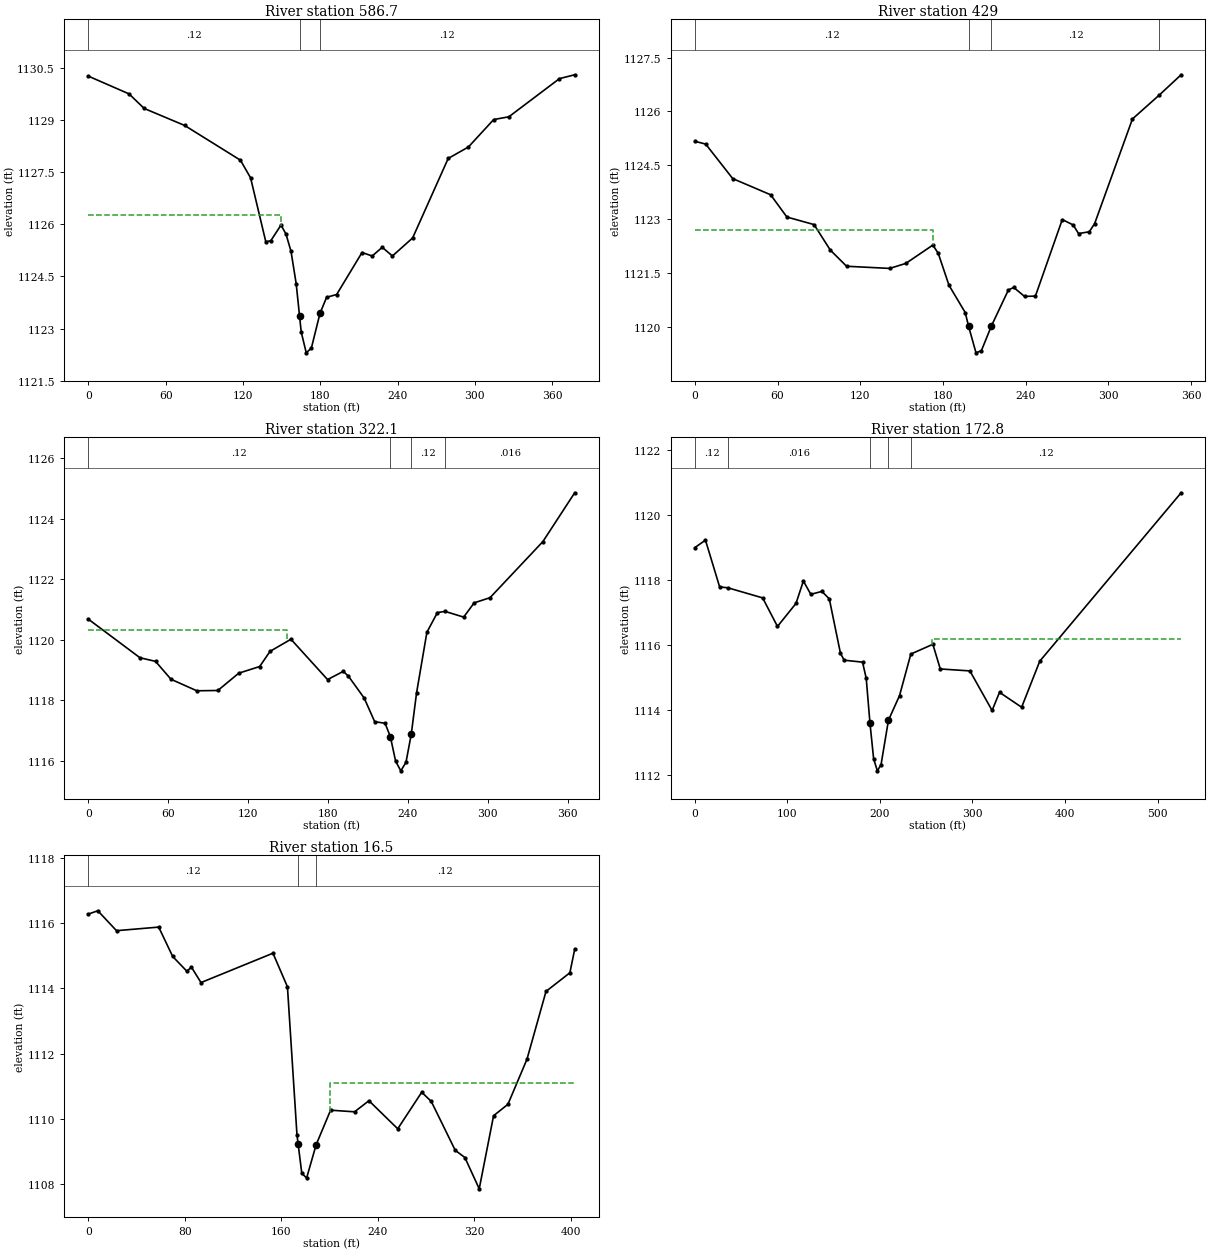
Type RM Length L Ch R = 1 ,586.7   ,168.8,157.8,146.2
XS GIS Cut Line= 4
     2344256.216      364389.781      2344169.25      364450.732
     2344267.201      364598.174     2344361.424      364600.197
#Sta/Elev= 30
       0 1130.27    31.5 1129.76    43.3 1129.34    74.7 1128.85     118 1127.85
   125.9 1127.34   137.7  1125.5   141.6 1125.53   149.5 1125.98   153.4 1125.72
   157.3 1125.22   161.3 1124.29  163.931123.351   165.2  1122.9   169.1  1122.3
   173.1 1122.44  179.761123.436   184.9  1123.9   192.7 1123.98   212.4 1125.19
   220.3 1125.09   228.1 1125.34     236 1125.09   251.7 1125.61   279.3  1127.9
     295 1128.23   314.6 1129.02   326.4  1129.1   365.7  1130.2   377.5 1130.31
#Mann= 3 ,-1 , 0
       0     .12       0  163.93    .045       0  179.76     .12       0
#XS Ineff= 2 , 0
          149.85 1126.27
Permanent Ineff=
       F       F
Bank Sta=163.93,179.76
XS Rating Curve= 0 ,0
Exp/Cntr=0.3,0.1

Type RM Length L Ch R = 1 ,429     ,107.5,106.9,106.1
XS GIS Cut Line= 4
     2344084.341      364490.302     2344022.817      364581.569
     2344178.373      364664.208     2344243.195      364679.364
#Sta/Elev= 30
       0 1125.17     7.9 1125.09    27.5 1124.13      55 1123.68    66.8 1123.06
    86.5 1122.85    98.3 1122.14   110.1 1121.69   141.4 1121.63   153.1 1121.77
   172.7 1122.28   176.6 1122.05   184.4 1121.16   196.2  1120.4  198.561120.027
     204 1119.28   207.9 1119.34   215.2 1120.03   227.5 1121.03   231.4  1121.1
   239.2 1120.85   247.1 1120.86   266.6 1122.99   274.5 1122.84   278.4  1122.6
   286.2 1122.65   290.1 1122.88   317.5 1125.79  337.121126.461   352.8 1127.02
#Mann= 4 ,-1 , 0
       0     .12       0  198.56    .045       0   215.2     .12       0
  337.12    .016       0
#XS Ineff= 2 , 0
          172.55 1122.71
Permanent Ineff=
       F       F
Bank Sta=198.56,215.2
XS Rating Curve= 0 ,0
Exp/Cntr=0.3,0.1

Type RM Length L Ch R = 1 ,322.1   ,136.8,149.3,160.5
XS GIS Cut Line= 4
     2343943.195      364584.572     2343929.341       364656.85
     2344112.669      364746.804     2344195.799      364719.989
#Sta/Elev= 30
       0 1120.68    38.7 1119.41    50.4 1119.29      62  1118.7    81.4 1118.32
    97.2 1118.33   112.9  1118.9   128.6 1119.12   136.4 1119.62   152.1 1120.02
   179.6 1118.69   191.4 1118.96   195.3  1118.8   207.1 1118.08     215  1117.3
   222.8 1117.25   226.8  1116.8   230.7    1116   234.6 1115.68   238.5 1115.96
   242.5  1116.9   246.4 1118.24   254.2 1120.25   262.1  1120.9  267.871120.938
   281.8 1120.75   289.7 1121.22   301.6 1121.39   341.3 1123.24   365.2 1124.85
#Mann= 4 ,-1 , 0
       0     .12       0   226.8    .045       0   242.5     .12       0
  267.87    .016       0
#XS Ineff= 2 , 0
          149.43 1120.32
Permanent Ineff=
       F       F
Bank Sta=226.8,242.5
XS Rating Curve= 0 ,0
Exp/Cntr=0.3,0.1

Type RM Length L Ch R = 1 ,172.8   ,162.1,156.3,150.4
XS GIS Cut Line= 4
     2343893.195      364637.697     2343879.762      364697.541
     2344042.262      364939.902     2344179.241      364835.519
#Sta/Elev= 30
       0    1119    11.5 1119.23    26.8 1117.79   35.92 1117.76    73.3 1117.45
    89.3 1116.57   109.3 1117.28   117.3 1117.97   125.3 1117.56   137.3 1117.65
   145.3 1117.42   157.3 1115.75   161.3 1115.53   181.2 1115.47   185.2 1114.97
   189.2  1113.6   193.2 1112.49   197.2 1112.12   201.2 1112.31   209.2 1113.68
   221.2 1114.44  233.391115.719   257.2 1116.02   265.2 1115.26   297.2  1115.2
   321.2 1113.98   329.2 1114.54   353.1 1114.08   372.7  1115.5   525.4 1120.69
#Mann= 5 ,-1 , 0
       0     .12       0   35.92    .016       0   189.2    .045       0
   209.2    .016       0  233.39     .12       0
#XS Ineff= 2 , 0
                          256.35         1116.17
Permanent Ineff=
       F       F
Bank Sta=189.2,209.2
XS Rating Curve= 0 ,0
Exp/Cntr=0.3,0.1

Type RM Length L Ch R = 1 ,16.5    ,11.2,16.5,21.9
XS GIS Cut Line= 4
     2343870.213      364816.769     2343821.681      364887.126
     2344004.853      365033.982      2344083.82       365008.01
#Sta/Elev= 30
       0 1116.28     7.8 1116.38    23.3 1115.77    58.3 1115.88    69.9 1114.98
    81.6 1114.53    85.5 1114.65    93.4 1114.18   153.1 1115.08   165.1 1114.05
     173 1109.52     1741109.225     177 1108.34     181 1108.19   188.9 1109.21
   200.9 1110.27   220.8 1110.22   232.7 1110.56   256.6  1109.7   276.5 1110.82
   284.4 1110.54   304.3 1109.04   312.3 1108.82   324.2 1107.86   336.1  1110.1
     348 1110.45   363.8 1111.83   379.6 1113.91   399.4 1114.48   403.4  1115.2
#Mann= 3 ,-1 , 0
       0     .12       0     174    .045       0   188.9     .12       0
#XS Ineff= 2 , 0
                          200.21         1111.11
Permanent Ineff=
       F       F
Bank Sta=174,188.9
XS Rating Curve= 0 ,0
Exp/Cntr=0.3,0.1

Chan Stop Cuts=-1
Use User Specified Reach Order=0
Composite Channel Slope=5